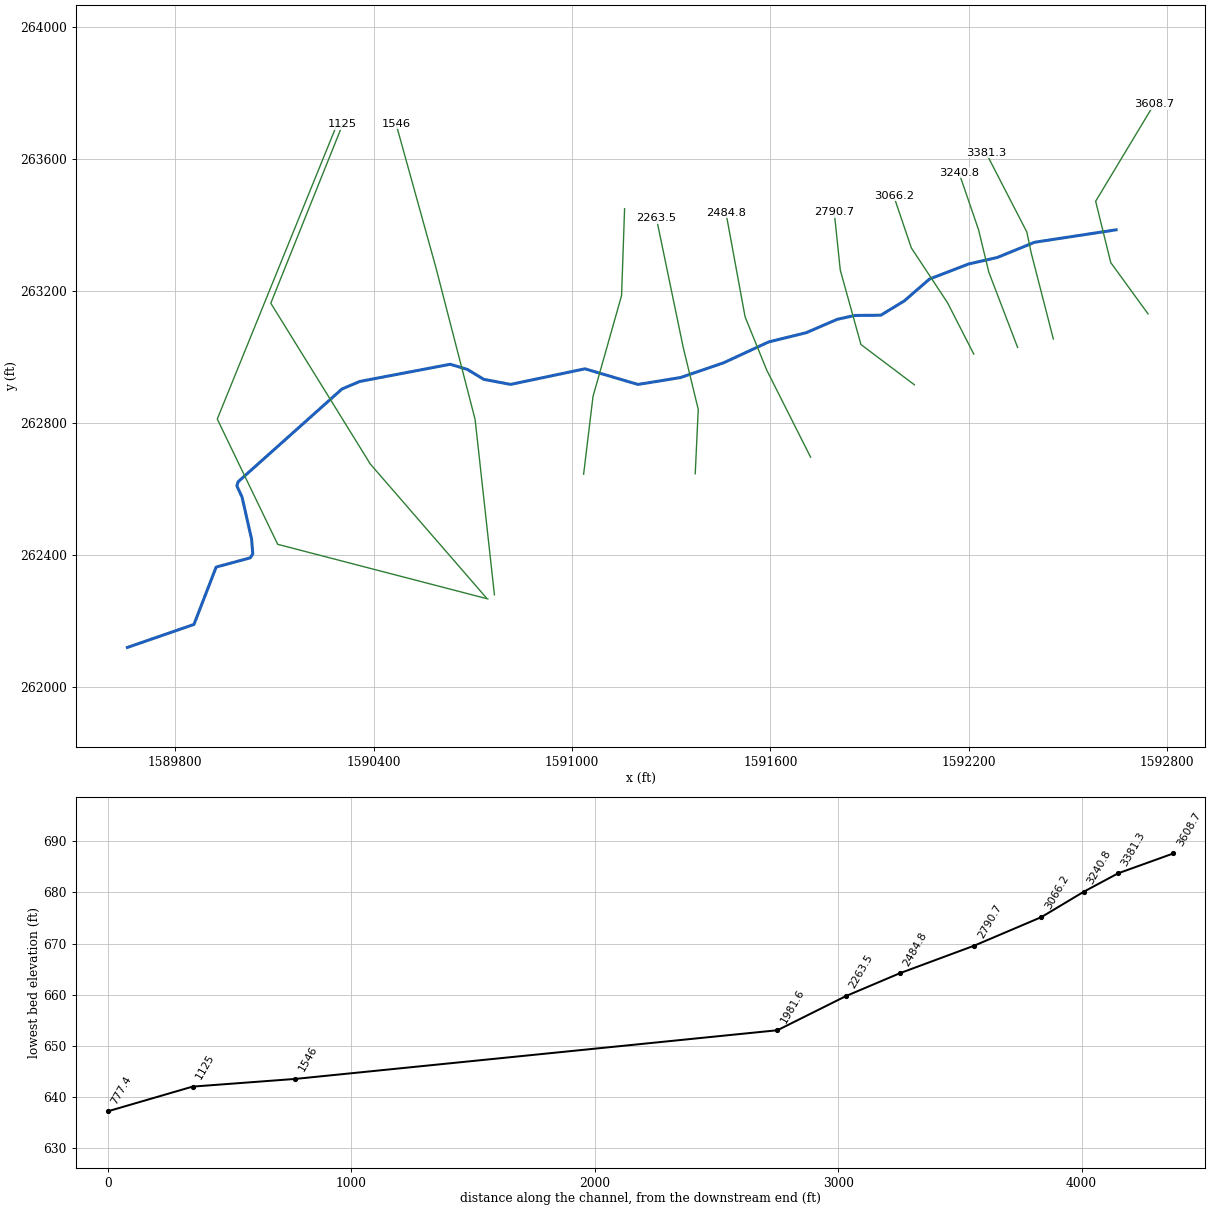
--- dnsbrnch.prj (project) ---

Proj Title=dnsbrnch
Current Plan=p01
Default Exp/Contr=0,0
English Units
Geom File=g01
Flow File=f01
Plan File=p01
BEGIN DESCRIPTION:
END DESCRIPTION:
DSS Export Rating Curves= 0
DSS Export Rating Curve Sorted= 0
DSS Export Volume Flow Curves= 0
DXF OffsetX= 0
DXF OffsetY= 0
DXF ScaleX= 0
DXF ScaleY= 0

--- dnsbrnch.p01 (plan) ---

Plan Title=Floodplain
Program Version=4.00
Geom File=g01
Flow File=f01
K Sum by GR=0
Std Step Tol=0.01
Critical Tol=0.01
Num of Std Step Trials=20
Max Error Tol=0.3
Flow Tol Ratio=0.001
Split Flow NTrial=30
Split Flow Tol=0.02
Split Flow Ratio=0.02
Log Output Level=0
Friction Slope Method=1
Unsteady Friction Slope Method=2
Unsteady Bridges Friction Slope Method=1
Global Log Level=0
CheckData=False
Run HTab=0
Run UNet=0
Run PostProcess=0
UNET Theta=0
UNET Theta Warmup=0
UNET ZTol=0
UNET ZSATol=0
UNET MxIter=0
UNET MaxInSteps=0
UNET DtIC=0
UNET DtMin=0
UNET MaxCRTS=0
UNET WFStab=0
UNET SFStab=0
UNET WFX=0
UNET SFX=0
UNET DSS MLevel=0
UNET DZMax Abort=0
UNET Convert EG Bridges=0
UNET Use Existing IB Tables=0
UNET Froude Limit=0
UNET Froude Power=0
Write IC File=0
Echo Input=False
Echo Output=False
Write Detailed=0

--- dnsbrnch.f01 (steady flow) ---

Flow Title=NFF Regression Equation
Program Version=4.00
Number of Profiles= 1
Profile Names=P100yr
River Rch & RM=dnsbrnch,Main            ,3608.7
     323
River Rch & RM=dnsbrnch,Main            ,3381.3
     323
River Rch & RM=dnsbrnch,Main            ,3240.8
     397
River Rch & RM=dnsbrnch,Main            ,2263.5
     415
Boundary for River Rch & Prof#=dnsbrnch,Main            , 1
Up Type= 0
Dn Type= 3
Dn Slope=0.006
DSS Import GetInterval= 0
DSS Import GetPeak= 0
DSS Import FillOption= 0

--- dnsbrnch.g01 (geometry) ---

Geom Title=USGS 10m DEM
Program Version=4.00

River Reach=dnsbrnch        ,Main
Reach XY= 30
     1592645.127      263386.222      1592398.78      263348.563
     1592285.469       263302.26     1592198.919      263282.657
     1592081.016      263237.062     1592004.626      263170.799
     1591933.796      263127.534     1591855.367      263126.804
     1591802.538      263115.276     1591708.374      263074.596
     1591594.249      263046.412     1591458.738      262983.423
     1591327.991      262938.622     1591199.559      262917.759
     1591039.277      262965.151      1590814.46      262917.892
     1590733.348       262933.26     1590683.676      262963.385
     1590631.809      262978.889     1590358.671      262926.882
     1590304.761      262904.078     1589990.949      262623.169
     1589986.843       262610.59     1590002.605      262576.242
     1590031.365      262449.223     1590034.998       262404.24
     1590027.509      262392.502     1589924.249      262364.475
     1589857.148      262190.703      1589655.85      262120.983

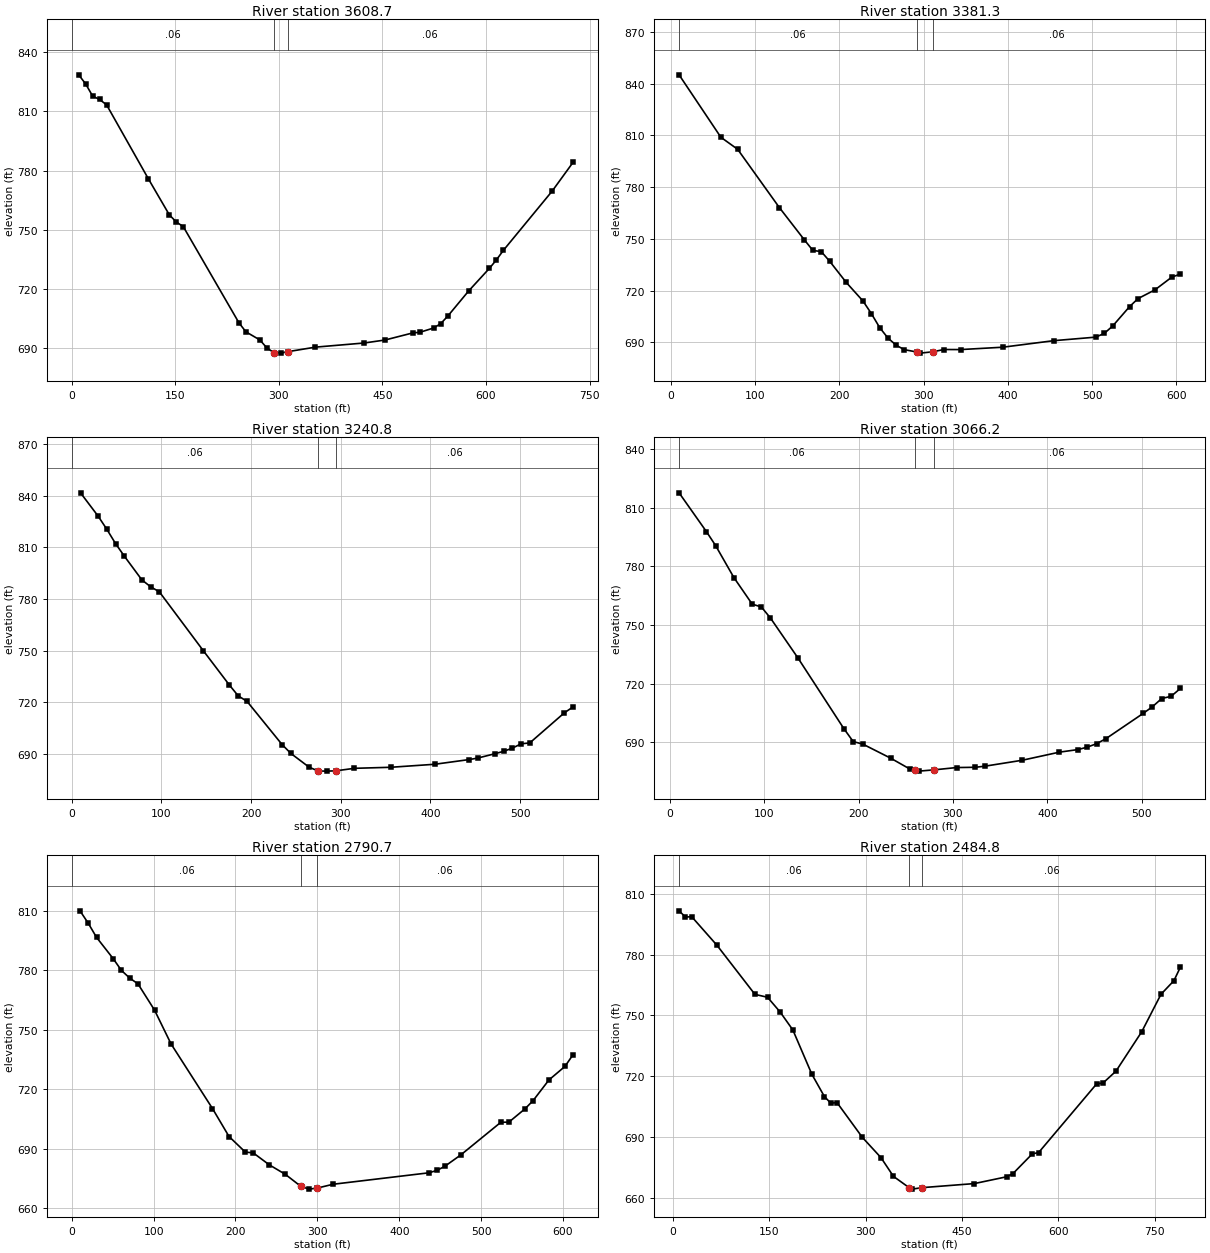
Type RM Length L Ch R = 1 ,3608.7  ,228.3,227.4,226.6
XS GIS Cut Line= 4
     1592741.701      263131.606     1592629.011      263286.935
     1592583.326      263472.719     1592759.974      263766.625
#Sta/Elev= 30
    10.1   828.5    20.2  823.87    30.3  817.74    40.4  816.01    50.5   813.3
   111.1  775.79   141.4   757.6   151.5  753.99   161.6  751.64   242.2  702.95
   252.3  698.39   272.5  694.28   282.5   690.3   292.7  687.86   302.7   687.6
   312.7  688.32     353  690.63   423.6  692.73   453.8  694.24   494.2  697.85
   504.2  698.14   524.4  700.34   534.5  702.53   544.6   706.3   574.8  719.02
   605.1  730.56   615.2  734.84   625.3  739.66   695.9  769.63   726.1  784.16
#Mann= 3 , 0 , 0
       0     .06       0   292.7    .045       0   312.7     .06       0
Bank Sta=292.7,312.7
XS Rating Curve= 0 ,0
Exp/Cntr=0.3,0.1

Type RM Length L Ch R = 1 ,3381.3  ,139.7,140.5,141.3
XS GIS Cut Line= 4
     1592455.409      263055.465     1592388.802      263314.916
     1592375.311      263379.482      1592251.35      263620.434
#Sta/Elev= 30
     9.9  845.17    59.5  808.95    79.4  801.97     129   768.1   158.7  749.35
   168.7  743.28   178.6  742.63   188.5  737.09   208.3  724.72   228.2  713.92
   238.1  706.65     248   698.5   257.9  692.39   267.9  688.17   277.3  685.71
  291.82  684.39   296.1  683.71  310.67  684.46   324.4  685.81   343.9  685.77
     394  687.14   454.3  690.92   504.4  692.99   514.5  695.16   524.5  699.44
   544.6  710.73   554.6  715.35   574.7  720.43   594.8  727.86   604.8  729.53
#Mann= 3 , 0 , 0
     9.9     .06       0  291.82    .045       0  310.67     .06       0
Bank Sta=291.82,310.67
XS Rating Curve= 0 ,0
Exp/Cntr=0.3,0.1

Type RM Length L Ch R = 1 ,3240.8  ,165.9,174.6,183.3
XS GIS Cut Line= 4
     1592347.364      263029.966     1592260.206      263258.248
     1592229.369      263386.165      1592170.05      263559.339
#Sta/Elev= 30
     9.8  841.61    29.3  828.18    39.1  820.49    48.9  812.12    58.6  804.91
    78.2  791.11      88  787.09    97.7  784.17   146.6  750.09   175.9  730.02
   185.7  723.78   195.5  720.61   234.6  695.53   244.4  690.39   264.6  682.46
   274.8  680.19   284.8  680.13   294.8  680.32   315.2  681.76   355.7  682.36
   404.8  684.11   443.4  686.85     453  687.74   472.3  690.28   481.9  691.67
   491.5  693.49   501.2  695.99   510.8   696.5   549.4  713.98     559  717.37
#Mann= 3 , 0 , 0
       0     .06       0   274.8    .045       0   294.8     .06       0
Bank Sta=274.8,294.8
XS Rating Curve= 0 ,0
Exp/Cntr=0.3,0.1

Type RM Length L Ch R = 1 ,3066.2  ,283.4,275.5,267.7
XS GIS Cut Line= 4
     1592214.802       263009.78     1592135.615      263165.108
     1592026.071      263331.343     1591972.391      263490.098
#Sta/Elev= 30
     9.7  817.73    38.7  797.85    48.4  790.72    67.8  774.32    87.2  760.71
    96.9  759.26   106.5  753.62   135.6  733.19   184.3  696.97   194.3  690.27
   204.2  689.06   234.1  681.76     254  676.32  260.26   675.6   263.9  675.16
  279.91  675.81   303.8  676.99   323.7  677.13   333.6  677.67   373.4  680.73
   412.9  684.89   432.6   686.2   442.4  687.47   452.3  689.22   462.2  691.81
   501.6  704.73   511.4  708.16   521.3  712.36   531.2  713.49     541   717.5
#Mann= 3 , 0 , 0
     9.7     .06       0  260.26    .045       0  279.91     .06       0
Bank Sta=260.26,279.91
XS Rating Curve= 0 ,0
Exp/Cntr=0.3,0.1

Type RM Length L Ch R = 1 ,2790.7  ,303,305.9,308.8
XS GIS Cut Line= 4
     1592035.108      262916.887     1591873.688      263038.713
     1591811.252      263264.092     1591792.978      263439.217
#Sta/Elev= 30
    10.1  810.01    20.2  803.73    30.3  796.62    50.6   785.9    60.7  779.94
    70.8  776.08    80.9  773.16   101.1  759.94   121.3  742.85   171.9  710.25
   192.1  696.14     212  688.28   221.7  687.87   241.2  681.87   260.7   677.1
   279.9  670.97   289.9  669.59   299.9  670.12   319.2  672.05   436.1  677.82
   445.9  679.01   455.7  681.12   475.2  686.86   524.1  703.33   533.9  703.39
   553.5  710.08   563.3  714.17   582.8  724.67   602.4  731.52   612.2  737.38
#Mann= 3 , 0 , 0
       0     .06       0   279.9    .045       0   299.9     .06       0
Bank Sta=279.9,299.9
XS Rating Curve= 0 ,0
Exp/Cntr=0.3,0.1

Type RM Length L Ch R = 1 ,2484.8  ,225,221.3,217.6
XS GIS Cut Line= 4
     1591721.406        262697.6     1591588.919      262961.049
     1591523.438      263122.469      1591465.57      263437.695
#Sta/Elev= 30
     9.8   801.7    19.7  798.63    29.5  798.79    68.8  784.65   127.8  760.42
   147.4     759   167.1  751.67   186.8  742.84   216.3  720.99   235.9  709.93
   245.7  706.71   255.6  706.91   294.9  689.78   323.9  679.75   343.3   670.5
  367.88  664.88   372.3   664.2  388.16  664.94   469.1  666.94   519.2  670.29
   529.2  671.87   559.2   681.6   569.2  682.29   659.4  716.22   669.4  716.66
   689.4  722.47   729.5  741.95   759.5  760.48   779.6  767.19   789.6  773.84
#Mann= 3 , 0 , 0
     9.8     .06       0  367.88    .045       0  388.16     .06       0
Bank Sta=367.88,388.16
XS Rating Curve= 0 ,0
Exp/Cntr=0.3,0.1

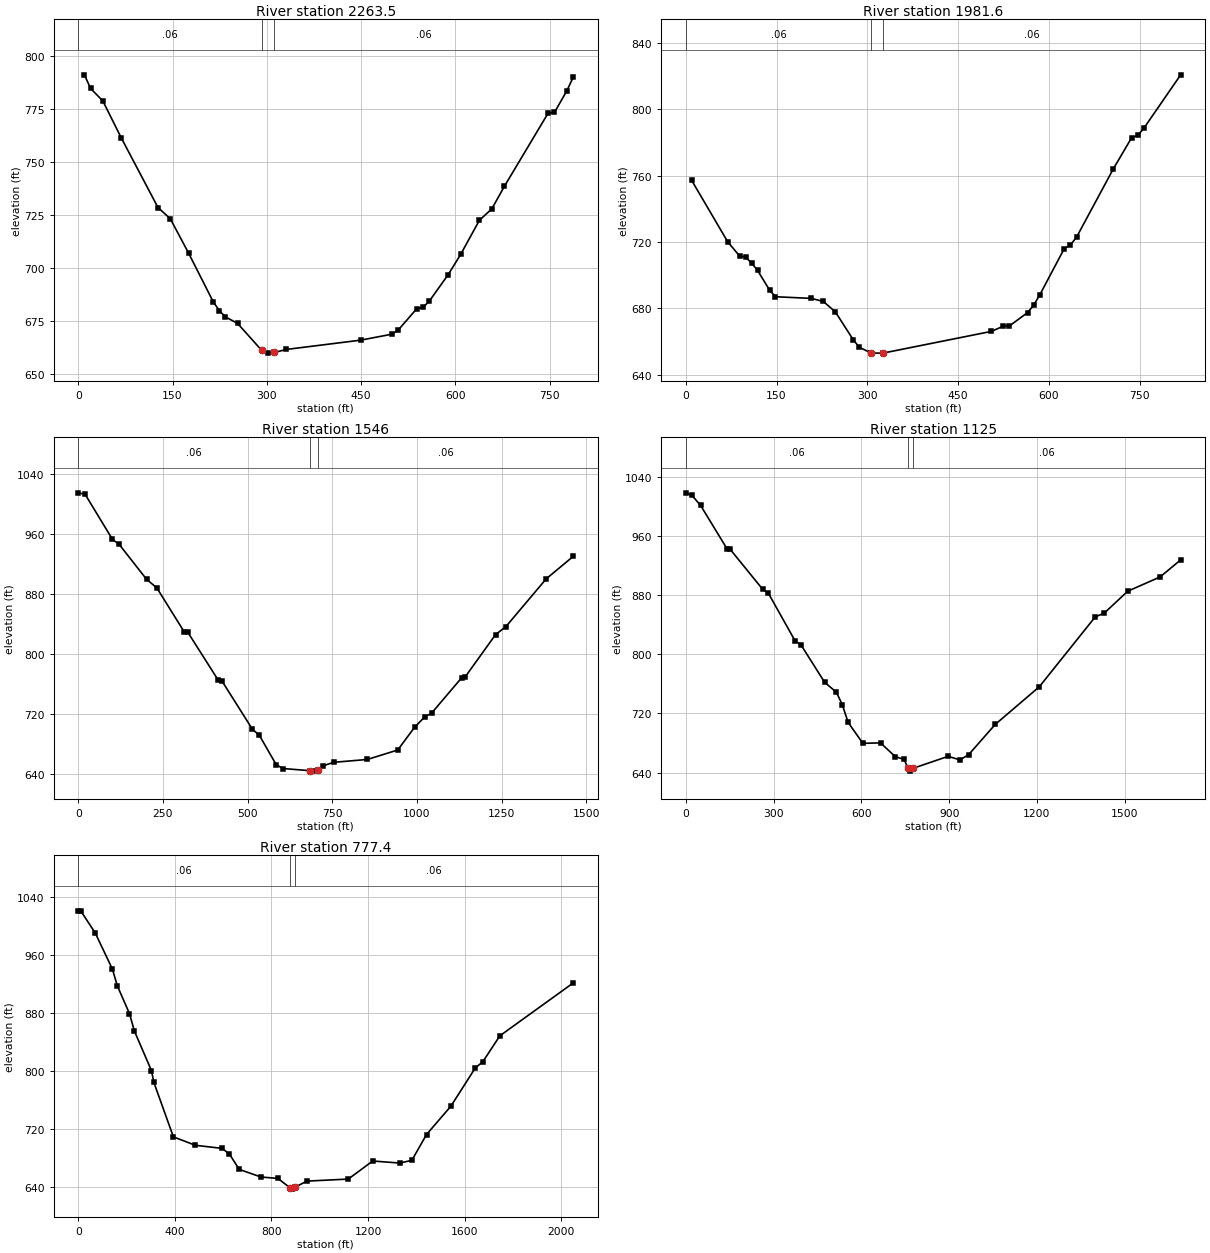
Type RM Length L Ch R = 1 ,2263.5  ,294.8,281.9,269
XS GIS Cut Line= 4
     1591372.678      262647.347     1591381.815      262842.269
      1591336.13      263031.099      1591255.42      263420.943
#Sta/Elev= 30
     9.8  790.95    19.5  784.55      39  778.66    68.3  761.28   126.8  728.39
   146.4  723.11   175.6  706.84   214.6  684.02   224.3  679.79     234  676.85
   253.4  673.77     292  660.99     302  659.74     312  660.04   331.1  661.48
   449.1  665.85   498.9  668.66   508.8  670.54   538.7  680.74   548.7  681.36
   558.6  684.28   588.5  696.71   608.4  706.27   638.2  722.35   658.1   727.8
     678  738.39   747.7  772.93   757.7  773.24   777.6  783.55   787.5  789.84
#Mann= 3 , 0 , 0
       0     .06       0     292    .045       0     312     .06       0
Bank Sta=292,312
XS Rating Curve= 0 ,0
Exp/Cntr=0.3,0.1

Type RM Length L Ch R = 1 ,1981.6  ,1965.4,1981.6,1996.2
XS GIS Cut Line= 4
     1591035.245      262645.951      1591063.67      262881.481
     1591149.964      263186.999     1591159.101      263450.004
#Sta/Elev= 30
     9.9  757.01    69.2  720.17      89  711.52    98.9  710.92   108.7  707.31
   118.6  702.92   138.4  691.07   148.3  687.02   207.6  686.01   227.4  684.16
   247.2  677.91   276.9  661.05   286.8  656.59   306.6  653.07   306.7  653.06
   326.6  653.12   505.1  666.15   524.9  669.31   534.9  669.44   564.8  677.43
     575  681.94   585.1  688.16   625.6  716.04   635.7   718.2   645.8  722.86
   706.5  763.94   736.9  782.79     747  784.16   757.1  788.48   817.9  820.63
#Mann= 3 , 0 , 0
       0     .06       0   306.6    .045       0   326.6     .06       0
Bank Sta=306.6,326.6
XS Rating Curve= 0 ,0
Exp/Cntr=0.3,0.1

Type RM Length L Ch R = 1 ,1546    ,416.1,421,426
XS GIS Cut Line= 4
     1590765.561      262280.458     1590707.156      262811.803
     1590587.708      263275.446     1590467.991      263707.538
#Sta/Elev= 30
       0 1014.72    20.2 1012.72   100.9  952.68     121  945.82   201.7  899.34
     232  887.92   312.7  829.38   322.7  829.32   413.5  764.72   423.6  764.25
   514.4   699.3   534.5  691.51   584.4  652.27   604.4  647.02   684.1  644.16
   694.1  643.55   706.8   644.4   724.1  650.79     754  655.29   853.7  659.11
   943.5  671.73   993.4  702.17  1023.3  715.93  1043.2  720.77  1132.9  768.39
  1142.9  769.34  1232.5   825.7  1262.4     836    1382  900.02  1461.7  929.92
#Mann= 3 , 0 , 0
       0     .06       0   684.1    .045       0   706.8     .06       0
Bank Sta=684.1,706.8
XS Rating Curve= 0 ,0
Exp/Cntr=0.3,0.1

Type RM Length L Ch R = 1 ,1125    ,349.8,347.6,345.4
XS GIS Cut Line= 4
     1590740.414      262272.076     1590390.455       262676.52
     1590089.488      263163.858     1590306.632      263705.443
#Sta/Elev= 30
       0 1018.05    20.2 1015.04    50.5 1001.16   141.3  942.23   151.4  941.91
   262.4  887.92   282.6  882.18   373.4  818.16   393.6  812.74   474.3   762.2
   514.7   748.6   534.8  731.91   554.9  707.82   605.2  679.61   665.5  680.23
   715.7   661.7   745.9  657.85  760.01  645.83     766  642.05     776  645.75
   896.6  662.04   936.8  657.24   966.9  664.37  1057.4  705.13  1208.2  756.08
  1399.4  850.55  1429.5  855.32    1510  885.09  1620.7  904.39  1691.1  927.44
#Mann= 3 , 0 , 0
       0     .06       0  760.01    .045       0     776     .06       0
#XS Ineff= 2 , 0
       0     759             778       0
Permanent Ineff=
       F       F
Bank Sta=760.01,776
XS Rating Curve= 0 ,0
Exp/Cntr=0.3,0.1

Type RM Length L Ch R = 1 ,777.4   ,779.6,777.4,775.2
XS GIS Cut Line= 4
     1590745.662      262268.004     1590110.312      262433.422
     1589927.605      262812.981      1590293.02      263713.943
#Sta/Elev= 30
       0 1020.79    10.1 1020.79    70.7  989.99   141.4   940.4   161.6  917.51
   212.1  879.08   232.3  855.18     303  800.63   313.1  784.27   393.9  709.29
   484.8  697.66   595.9  693.39   626.2  685.48   666.6  664.43   756.8  653.95
     827  651.98   877.2  639.03   887.2  637.24   897.2  639.87   947.4   648.3
  1118.3  651.09  1219.6     676    1331  673.19  1381.6  676.89  1442.4   712.5
  1543.6  751.65  1644.9  804.51  1675.3  812.63  1746.2  848.54    2050  921.38
#Mann= 3 , 0 , 0
       0     .06       0   877.2    .045       0   897.2     .06       0
#XS Ineff= 2 , 0
       0     871             899       0
Permanent Ineff=
       F       F
Bank Sta=877.2,897.2
XS Rating Curve= 0 ,0
Exp/Cntr=0.3,0.1

Chan Stop Cuts=-1
Use User Specified Reach Order=0